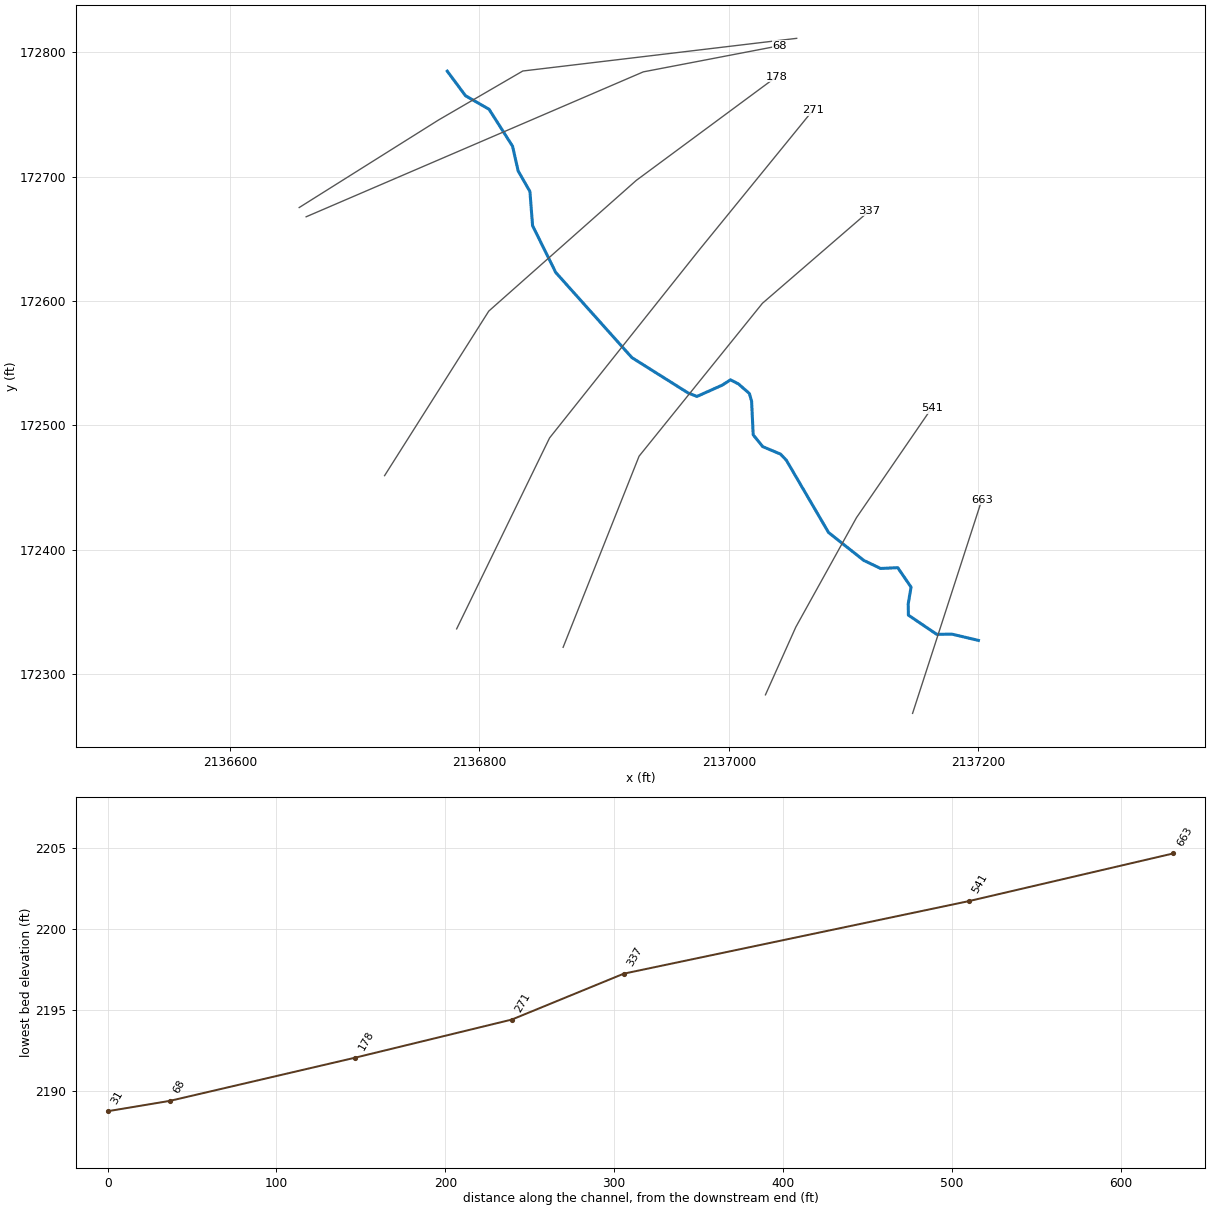
--- SFRKPTTSCKT1.prj (project) ---

Proj Title=SFRKPTTSCKT1
Current Plan=p01
Default Exp/Contr=0,0
English Units
Geom File=g01
Flow File=f01
Plan File=p01
Background Map Layer=Inundation Boundary (01pct Value_0)
BEGIN DESCRIPTION:
Stream Name: South Fork Potts Creek Tributary
Flood Zone: Approximate
Monroe County, West Virginia
HEC-RAS Version: 5.0.7
Vertical Datum: NAVD88
Projection: NAD 1983 StatePlane West Virginia S FIPS 4702 (US Feet)
LiDAR: 2016, 1-meter
Land Use: 2016 NLCD
Hydrology Method:
Regression.
Model Notes:
END DESCRIPTION:
DSS Export Rating Curves= 0
DSS Export Rating Curve Sorted= 0
DSS Export Volume Flow Curves= 0
DXF OffsetX= 0
DXF OffsetY= 0
DXF ScaleX= 0
DXF ScaleY= 0

--- SFRKPTTSCKT1.p01 (plan) ---

Plan Title=Floodplain
Program Version=5.07
Short Identifier=Floodplain
Geom File=g01
Flow File=f01
Subcritical Flow
K Sum by GR= 0
Std Step Tol= 0.01
Critical Tol= 0.01
Num of Std Step Trials= 20
Max Error Tol= 0.3
Flow Tol Ratio= 0.001
Split Flow NTrial= 30
Split Flow Tol= 0.02
Split Flow Ratio= 0.02
Log Output Level= 0
Friction Slope Method= 1
Unsteady Friction Slope Method= 2
Unsteady Bridges Friction Slope Method= 1
Parabolic Critical Depth
Global Vel Dist= 0 , 0 , 0
Global Log Level= 0
CheckData=True
Encroach Param=-1 ,0,0, 0
Mapping Interval=1HOUR
Computation Time Step Use Courant=        0
Computation Time Step Use Time Series=    0
Computation Time Step Count To Double=0
Computation Time Step Max Doubling=0
Computation Time Step Max Halving=0
Computation Time Step Residence Courant=0
Run HTab= 0
Run UNet= 0
Run Sediment= 0
Run PostProcess= 0
Run WQNet= 0
Run RASMapper=-1
UNET Theta= 0
UNET Theta Warmup= 0
UNET ZTol= 0
UNET ZSATol= 0
UNET MxIter= 0
UNET Max Iter WO Improvement= 0
UNET MaxInSteps= 0
UNET DtIC= 0
UNET DtMin= 0
UNET MaxCRTS= 0
UNET WFStab= 0
UNET SFStab= 0
UNET WFX= 1
UNET SFX= 1
UNET 1D Methodology=Finite Difference
UNET DSS MLevel= 1
UNET Pardiso=0
UNET DZMax Abort= 0
UNET Use Existing IB Tables= 0
UNET Froude Reduction=False
UNET Froude Limit= 0
UNET Froude Power= 0
UNET D1 Cores= 0
UNET D2 Coriolis=0
UNET D2 Cores= 0
UNET D2 Theta= 1
UNET D2 Theta Warmup= 1
UNET D2 Z Tol= 0.01
UNET D2 Volume Tol= 0.01
UNET D2 Max Iterations= 20
UNET D2 Equation= 0
UNET D2 RampUpFraction=0.1
UNET D2 TimeSlices= 1
UNET D2 BCVolumeCheck=0
UNET D1D2 MaxIter= 0
UNET D1D2 ZTol=0.01
UNET D1D2 QTol=0.1
UNET D1D2 MinQTol=1
Write IC File= 0
Write IC File at Fixed DateTime=0
Write IC File at Sim End=0
Echo Input=False
Echo Parameters=False
Echo Output=False
Write Detailed= 0
HDF Write Warmup=0
HDF Write Time Slices=0
HDF Flush=0
HDF Face Node Velocities=0
HDF Compression= 1
HDF Chunk Size= 1
HDF Spatial Parts= 1
HDF Use Max Rows=0
HDF Fixed Rows= 1
Calibration Method= 0
Calibration Iterations= 20
Calibration Max Change=0.05
Calibration Tolerance=0.2
Calibration Maximum=1.5
Calibration Minimum=0.5
Calibration Optimization Method= 1
WQ AD Non Conservative
WQ ULTIMATE=-1
WQ Max Comp Step=1HOUR
WQ Output Interval=15MIN
WQ Output Selected Increments= 0
WQ Output face flow=0
WQ Output face velocity=0
WQ Output face area=0
WQ Output face dispersion=0
WQ Output cell volume=0
WQ Output cell surface area=0
WQ Output cell continuity=0
WQ Output cumulative cell continuity=0
WQ Output face conc=0
WQ Output face dconc_dx=0
WQ Output face courant=0
WQ Output face peclet=0
WQ Output face adv mass=0
WQ Output face disp mass=0
WQ Output cell mass=0
WQ Output cell source sink temp=0
WQ Output nsm pathways=0
WQ Output nsm derived pathways=0
WQ Output MaxMinRange=-1
WQ Daily Max Min Mean=-1
WQ Daily Range=0
WQ Daily Time=0
WQ Create Restart=0
WQ Fixed Restart=0
WQ System Summary=0
WQ Write To DSS=0
WQ Use Fixed Temperature=0
Sorting and Armoring Iterations= 10
XS Update Threshold= 0.02
Bed Roughness Predictor= 0
Hydraulics Update Threshold= 0.02
Energy Slope Method= 1
Volume Change Method= 1
Sediment Retention Method= 0
XS Weighting Method= 0
Number of US Weighted Cross Sections= 1
Number of DS Weighted Cross Sections= 1
Upstream XS Weight=0
Main XS Weight=1
Downstream XS Weight=0
Number of DS XS's Weighted with US Boundary= 1
Upstream Boundary Weight= 1
Weight of XSs Associated with US Boundary= 0
Number of US XS's Weighted with DS Boundary= 1
Downstream Boundary Weight= 0.5
Weight of XSs Associated with DS Boundary= 0.5
Percentile Method= 0
Sediment Output Level= 3
Mass or Volume Output= 0
Output Increment Type= 1
Profile and TS Output Increment= 1
XS Output Flag= 0
XS Output Increment= 10
Write Gradation File= 0
Read Gradation Hotstart= 0
Write HDF5 File= 1
Write Binary Output= 1
Write DSS Sediment File= 0
SV Curve= 0
Specific Gage Flag= 0

--- SFRKPTTSCKT1.f01 (steady flow) ---

Flow Title=Flow
Program Version=5.07
Number of Profiles= 6
Profile Names=01pct,10pct,04pct,02pct,0_2pct,01plus
River Rch & RM=SFRKPTTSCKT1,Main            ,663
     316     163     220     266     447     468
Boundary for River Rch & Prof#=SFRKPTTSCKT1,Main            , 1
Up Type= 0
Dn Type= 3
Dn Slope=0.02037
Boundary for River Rch & Prof#=SFRKPTTSCKT1,Main            , 2
Up Type= 0
Dn Type= 3
Dn Slope=0.02037
Boundary for River Rch & Prof#=SFRKPTTSCKT1,Main            , 3
Up Type= 0
Dn Type= 3
Dn Slope=0.02037
Boundary for River Rch & Prof#=SFRKPTTSCKT1,Main            , 4
Up Type= 0
Dn Type= 3
Dn Slope=0.02037
Boundary for River Rch & Prof#=SFRKPTTSCKT1,Main            , 5
Up Type= 0
Dn Type= 3
Dn Slope=0.02037
Boundary for River Rch & Prof#=SFRKPTTSCKT1,Main            , 6
Up Type= 0
Dn Type= 3
Dn Slope=0.02037
DSS Import GetInterval= 0
DSS Import GetPeak= 0
DSS Import FillOption= 0

--- SFRKPTTSCKT1.g01 (geometry) ---

Geom Title=Geometry
Program Version=5.07

River Reach=SFRKPTTSCKT1    ,Main
Reach XY= 30
     2137200.059      172327.019     2137178.736      172332.081
     2137166.662      172331.882     2137143.919      172347.332
     2137143.768      172356.491     2137146.046      172369.856
     2137135.376      172385.505     2137121.644      172384.862
     2137108.211      172391.304     2137079.938      172413.742
     2137046.078      172471.904     2137041.415      172476.825
     2137027.157      172482.837     2137019.504      172492.289
     2137018.225      172519.338     2137016.457      172525.555
     2137007.583      172533.322     2137001.283      172536.549
      2136994.69      172532.276     2136974.433      172523.196
     2136967.307      172525.994     2136922.278      172554.403
     2136861.177      172622.943     2136842.649      172660.535
      2136840.53      172687.987     2136831.095      172704.489
     2136826.602      172724.405     2136807.788       172754.08
     2136788.867      172765.012     2136774.249      172784.741

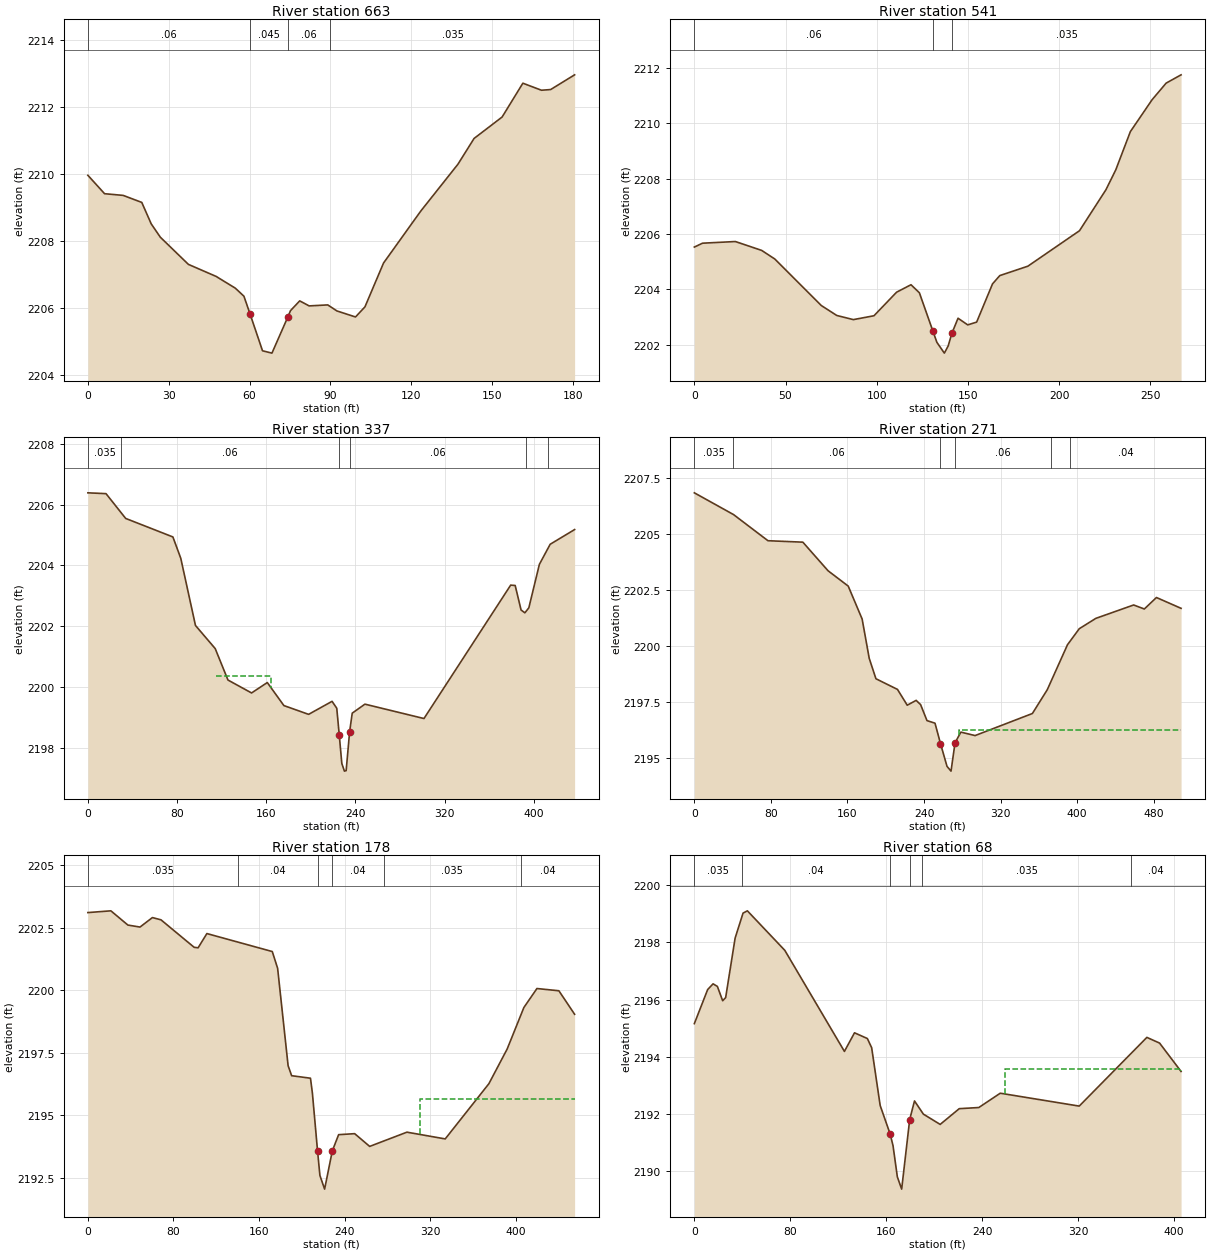
Type RM Length L Ch R = 1 ,663     ,111.6,121.1,97.9
XS GIS Cut Line= 2
     2137147.265      172268.348     2137202.821      172440.223
#Sta/Elev= 30
       0 2209.95     6.2  2209.4    13.1 2209.35      20 2209.14    23.5  2208.5
    26.9  2208.1    37.3 2207.29    47.6 2206.93    54.7 2206.58    57.9 2206.34
    60.22205.804    64.8 2204.71    68.3 2204.64    74.22205.721    75.2 2205.91
    78.6  2206.2    82.1 2206.05      89 2206.08    92.4  2205.9    99.3 2205.72
   102.8 2206.02   109.7 2207.33   123.5 2208.88   137.3 2210.28   143.3 2211.05
   153.7 2211.69   161.4  2212.7   168.3 2212.49   171.7 2212.51   180.6 2212.95
#Mann= 4 ,-1 , 0
       0     .06       0    60.2    .045       0    74.2     .06       0
      90    .035       0
Bank Sta=60.2,74.2
XS Rating Curve= 0 ,0
Exp/Cntr=0.5,0.1

Type RM Length L Ch R = 1 ,541     ,174.3,204.5,173.8
XS GIS Cut Line= 4
2137029.32260514172283.2496289572137053.64992508 172337.69648787
2137102.30456496172425.7382171772137162.54364291172513.779946483
#Sta/Elev= 30
       0 2205.53     4.5 2205.67    22.5 2205.73    36.9 2205.41    44.1  2205.1
    69.6 2203.42    78.1 2203.06    87.2 2202.91    98.5 2203.05   110.9  2203.9
   118.8 2204.17   123.4 2203.88   130.82202.498     133 2202.09   137.1  2201.7
   139.2 2201.96   141.22202.413   144.6 2202.96   149.9 2202.72   154.8 2202.82
   163.5  2204.2   167.5  2204.5   182.9 2204.84   211.2 2206.12   225.7  2207.6
   231.1 2208.32   239.1  2209.7     251 2210.85   258.7 2211.45   266.9 2211.75
#Mann= 3 ,-1 , 0
       0     .06       0   130.8    .045       0   141.2    .035       0
Bank Sta=130.8,141.2
XS Rating Curve= 0 ,0
Exp/Cntr(USF)=0,0
Exp/Cntr=0.5,0.3

Type RM Length L Ch R = 1 ,337     ,66.7,66.3,66.3
XS GIS Cut Line= 4
2136867.14047221172321.4782745772136928.02968248172475.150496775
2137026.90303764172598.0970161292137112.73055922172672.486747995
#Sta/Elev= 30
       02206.394  16.2772206.367  33.922 2205.55  76.269 2204.94  83.3272204.239
  96.5242202.023 114.2172201.262 125.6752200.225 146.8492199.799 160.9652200.142
  175.862199.383  198.022199.094 219.0712199.523 223.2812199.294 225.4792198.424
 227.8132197.474 230.1462197.223 231.702 2197.24 234.8132198.522 237.1472199.133
 248.542 2199.43 301.5042198.956 379.3052203.353 383.335 2203.34 388.6082202.534
 392.018 2202.44 395.5852202.605 405.0432204.037 414.7292204.699 436.6462205.183
#Mann= 6 ,-1 , 0
       0    .035       0      30     .06       0 225.479    .045       0
 234.813     .06       0  393.07     .04       0  413.07    .035       0
#XS Ineff= 3 ,-1
  115.25  164.41 2200.36  164.41     202 2199.12     260   432.8 2199.12
Permanent Ineff=
       F       F       F
Bank Sta=225.479,234.813
XS Rating Curve= 0 ,0
Exp/Cntr(USF)=0,0
Exp/Cntr=0.3,0.3

Type RM Length L Ch R = 1 ,271     ,96,92.9,82.6
XS GIS Cut Line= 4
2136781.79928241172336.303469831 2136856.2846706172489.834576105
2136975.56498535172640.1766411672137067.57995548172753.573654702
#Sta/Elev= 30
       0 2206.83  40.9612205.858  76.919 2204.69 113.3842204.625 139.7222203.347
 160.7892202.662 175.3212201.192 182.7492199.431 189.7552198.521 212.2722198.045
 222.4482197.339 231.7892197.555  236.462197.363 243.086 2196.65 251.4622196.536
   257.22195.626 264.0262194.606 268.2142194.393 272.402 2195.66 278.4942196.136
 293.3422195.982 353.2222196.968 368.7812198.031 389.9062200.042 402.2142200.757
 419.4822201.219 459.0372201.818 470.1832201.638 482.8582202.152 508.5912201.668
#Mann= 6 ,-1 , 0
       0    .035       0      40     .06       0   257.2    .045       0
 272.402     .06       0  372.56    .035       0  392.56     .04       0
#XS Ineff= 2 , 0
          252.72 2196.22  276.79         2196.25
Permanent Ineff=
       F       F
Bank Sta=257.2,272.402
XS Rating Curve= 0 ,0
Exp/Cntr(USF)=0,0
Exp/Cntr=0.3,0.3

Type RM Length L Ch R = 1 ,178     ,112,109.6,93.5
XS GIS Cut Line= 4
2136724.03373838172459.511487916 2136807.5459524172591.817355075
2136925.77672731172696.9113772152137038.37746531172780.423591237
#Sta/Elev= 30
       0 2203.11    21.5 2203.18    37.4 2202.61    48.7 2202.53    60.3 2202.91
    68.3 2202.82    99.3 2201.72     103  2201.7   111.2 2202.27   172.3 2201.55
   177.3 2200.88   187.1 2196.98   190.4 2196.58     208 2196.48   209.8 2195.88
   214.62193.572   216.8 2192.59   221.2 2192.04   228.4 2193.57   234.3 2194.22
   249.3 2194.26   263.3 2193.75   298.1 2194.32   333.9 2194.05   374.7 2196.26
   391.8 2197.65   407.4 2199.31   419.6 2200.07   440.1 2199.98   454.8 2199.04
#Mann= 6 ,-1 , 0
       0    .035       0     140     .04       0   214.6    .045       0
   228.4     .04       0  276.46    .035       0  404.65     .04       0
#XS Ineff= 2 , 0
                          310.17         2195.65
Permanent Ineff=
       F       F
Bank Sta=214.6,228.4
XS Rating Curve= 0 ,0
Exp/Cntr(USF)=0,0
Exp/Cntr=0.3,0.1

Type RM Length L Ch R = 1 ,68      ,32.8,36.9,37.4
XS GIS Cut Line= 3
     2136661.154      172667.6532136931.40676421172784.176949171
2137040.83781919  172805.2280369
#Sta/Elev= 30
       0 2195.16    11.1 2196.35    15.6 2196.55    19.2 2196.46    23.6 2195.96
    26.1 2196.07      34 2198.15    40.6 2199.02    44.2  2199.1    75.4 2197.72
   125.1 2194.19   133.5 2194.84   144.2 2194.64   147.8 2194.32   154.9  2192.3
   163.22191.306   165.6  2190.9   169.2 2189.81   172.8 2189.38   179.52191.811
   183.5 2192.46   190.9    2192   204.9 2191.64   220.8 2192.19   237.1 2192.23
     255 2192.73   320.8 2192.28   377.2 2194.68   387.8 2194.48   405.7 2193.49
#Mann= 6 ,-1 , 0
       0    .035       0      40     .04       0   163.2    .045       0
   179.5     .04       0     190    .035       0   364.3     .04       0
#XS Ineff= 2 , 0
                          259.31         2193.58
Permanent Ineff=
       F       F
Bank Sta=163.2,179.5
XS Rating Curve= 0 ,0
Exp/Cntr=0.3,0.1

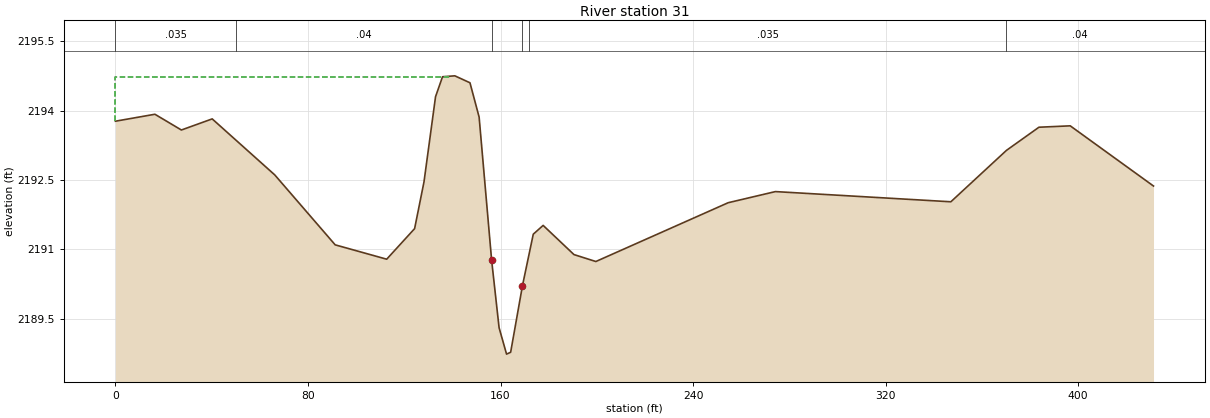
Type RM Length L Ch R = 1 ,31      ,,,
XS GIS Cut Line= 4
2136655.58029272172675.0822914012136767.24269124172745.457752655
2136834.80313404172784.8680109582137054.37457316172811.141516493
#Sta/Elev= 30
       0 2193.77    16.4 2193.92    27.4 2193.58    40.2 2193.82    66.2 2192.61
    91.3  2191.1   112.7 2190.79   124.3 2191.45   128.2 2192.46     133  2194.3
   135.9 2194.73     141 2194.75   147.3  2194.6   151.1 2193.86   156.32190.767
   159.4 2189.31   162.5 2188.74   164.2 2188.78 169.1152190.219   173.6 2191.33
   177.7 2191.52   190.5 2190.89   199.6 2190.74   254.6 2192.01   274.2 2192.25
   347.1 2192.03   370.2 2193.14   383.7 2193.64   396.7 2193.67   431.3 2192.37
#Mann= 6 ,-1 , 0
       0    .035       0      50     .04       0   156.3    .045       0
 169.115     .04       0  171.99    .035       0   370.2     .04       0
#XS Ineff= 2 , 0
          138.97 2194.73
Permanent Ineff=
       F       F
Bank Sta=156.3,169.115
XS Rating Curve= 0 ,0
Exp/Cntr(USF)=0,0
Exp/Cntr=0.5,0.1
LCMann Table=0

Chan Stop Cuts=-1
Use User Specified Reach Order=0
Composite Channel Slope=5